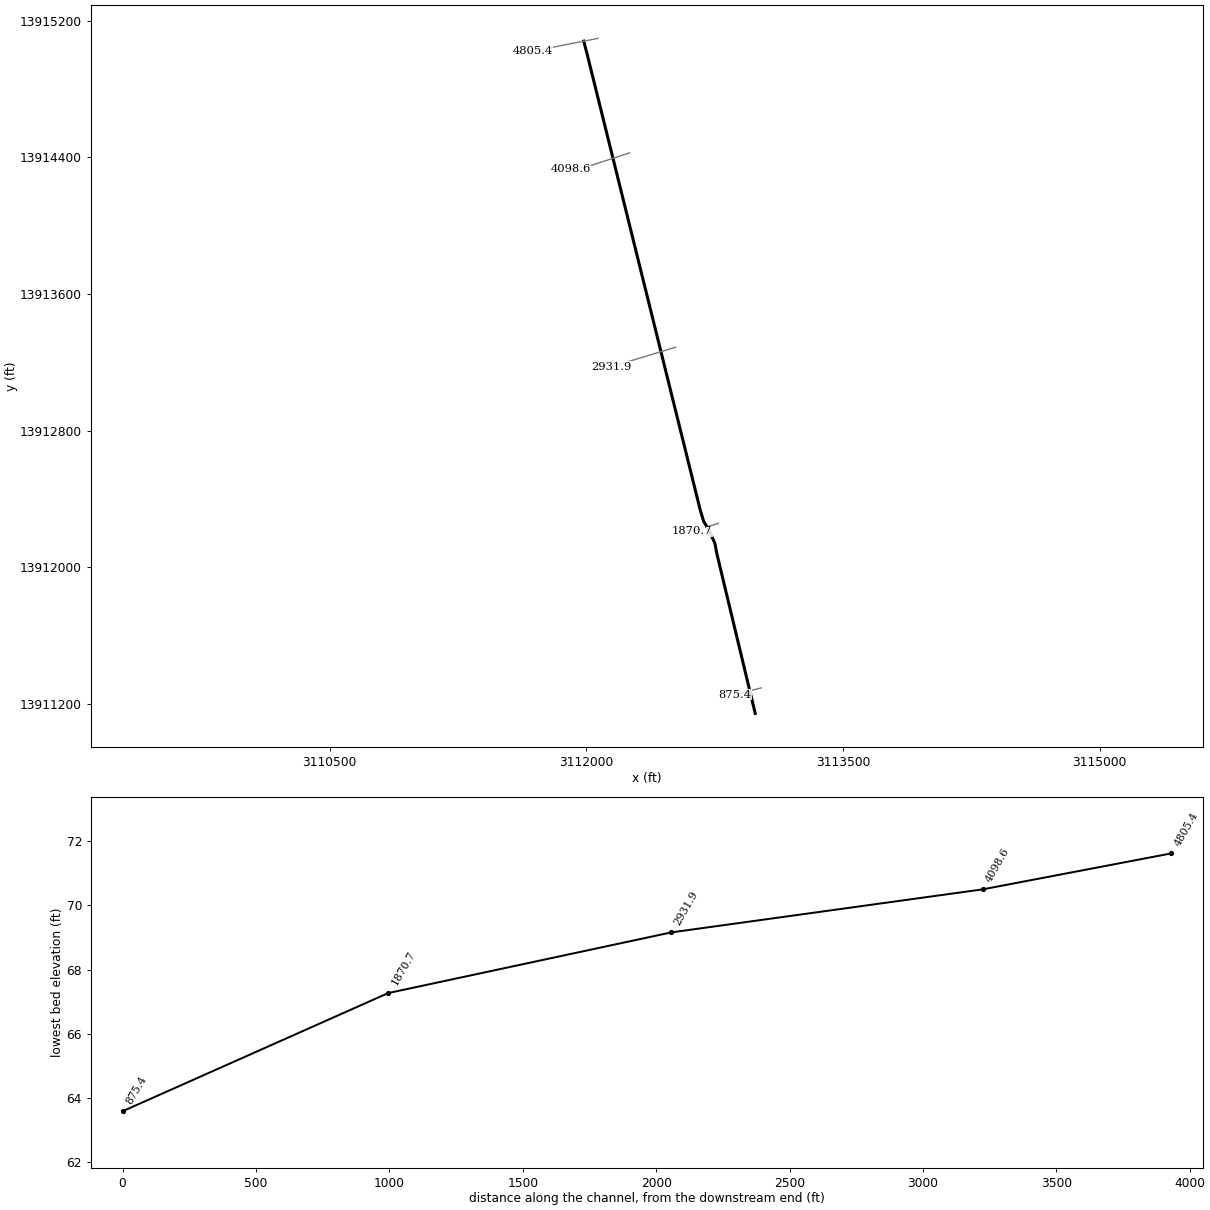
--- P156-00-00.PRJ (project) ---

Proj Title=P156-00-00
Current Plan=p02
Default Exp/Contr=.3,.1
English Units
Geom File=g01
Flow File=f01
Flow File=f02
Plan File=p01
Plan File=p02
Y Axis Title=Elevation
X Axis Title(PF)=Main Channel Distance
X Axis Title(XS)=Station
BEGIN DESCRIPTION:
Greens Bayou Watershed
P156-00-00
HCFCD Unit P156-00-00
Flood Hazard Model
10, 2, 1, 0.2% Event
Filename P156-00-00.prj
Prepared by:  Watershed Concepts  Date:
Reviewed by:                      Date:
STATUS FINAL
END DESCRIPTION:
DSS File=dss
DSS Export Rating Curves= 0
DSS Export Rating Curve Sorted= 0
DSS Export Volume Flow Curves= 0
DXF OffsetX= 0
DXF OffsetY= 0
DXF ScaleX= 1
DXF ScaleY= 10

--- P156-00-00.p02 (plan) ---

Plan Title=Floodway
Version=Version 3.0.1  Mar 2001
Short Identifier=Floodway0607
Geom File=g01
Flow File=f02
Subcritical Flow
K Sum by GR= 0
Std Step Tol= 0.01
Critical Tol= 0.01
Num of Std Step Trials= 20
Max Error Tol= 0.3
Flow Tol Ratio= 0.001
Split Flow NTrial= 30
Split Flow Tol= 0.02
Split Flow Ratio= 0.02
Log Output Level= 0
Friction Slope Method= 1
Unsteady Friction Slope Method= 2
Parabolic Critical Depth
Global Vel Dist= 0 , 0 , 0
Global Log Level= 0
CheckData=True
Encroach Param=-1 ,0,0, 2
Encroach River=P156-00-00
Encroach Reach=Reach - 1
Encroach Node=4805.4
       1  4949.8  5048.5
Encroach Node=4098.6
       1  4949.8  5048.5
Encroach Node=2931.9
       1  4957.2  5042.4
Encroach Node=1870.7
       1  4969.6  5032.9
Encroach Node=875.4
       1  4971.8  5032.4
Encroach Reach=P156-00-00_0009
Encroach Node=4805.4
       1  4949.8  5048.5
Encroach Node=4098.6
       1  4949.8  5048.5
Encroach Node=2931.9
       1  4957.2  5042.4
Encroach Node=1870.7
       1  4969.6  5032.9
Encroach Node=875.4
       1  4971.8  5032.4
Computation Interval=1HOUR
Output Interval=1HOUR
Run HTab= 0
Run UNet= 0
Run PostProcess= 0
UNET Theta= 1
UNET ZTol= 0.02
UNET ZSATol= 0.1
UNET MxIter= 20
UNET MaxInSteps= 20
UNET DtIC= 0
UNET DtMin= 0
UNET MaxCRTS= 20
UNET WFStab= 2
UNET SFStab= 1
UNET WFX= 1
UNET SFX= 1
UNET Convert EG Bridges=-1
UNET Use Existing IB Tables=-1
Instantaneous Interval=1HOUR
Write IC File= 0
Write Velocity= 0
Write Detailed= 0

--- P156-00-00.p01 (plan) ---

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Plan Title=FEMA Effective June 2007
Short Identifier=FEMAeff0607
Geom File=g01
Flow File=f01
Encroach Param=-1 ,0,0, 0
DSS File=dss

--- P156-00-00.f02 (steady flow) ---

Flow Title= Floodway
Number of Profiles= 2
Profile Names=1PCT_100yr, 1PCTFloodway_100yrFW
River Rch & RM=P156-00-00,P156-00-00_0009,4805.4
    1557    1557
River Rch & RM=P156-00-00,P156-00-00_0009,2931.9
    1816    1816
River Rch & RM=P156-00-00,P156-00-00_0009,1870.7
    2098    2098
Boundary for River Rch & Prof#=P156-00-00,P156-00-00_0009, 1
Up Type= 0
Dn Type= 3
Dn Slope= 0.00400
Boundary for River Rch & Prof#=P156-00-00,P156-00-00_0009, 2
Up Type= 0
Dn Type= 1
Dn Known WS=75.64

--- P156-00-00.f01 (steady flow) ---

Flow Title= FEMA Effective June 2007
Number of Profiles= 4
Profile Names=10PCT_10yr, 2PCT_50yr, 1PCT_100yr, 0.2PCT_500yr
River Rch & RM=P156-00-00,P156-00-00_0009,4805.4
     917    1340    1557    2166
River Rch & RM=P156-00-00,P156-00-00_0009,2931.9
    1074    1565    1816    2518
River Rch & RM=P156-00-00,P156-00-00_0009,1870.7
    1246    1809    2098    2900
Boundary for River Rch & Prof#=P156-00-00,P156-00-00_0009, 1
Up Type= 0
Dn Type= 3
Dn Slope= 0.00400
Boundary for River Rch & Prof#=P156-00-00,P156-00-00_0009, 2
Up Type= 0
Dn Type= 3
Dn Slope= 0.00400
Boundary for River Rch & Prof#=P156-00-00,P156-00-00_0009, 3
Up Type= 0
Dn Type= 3
Dn Slope= 0.00400
Boundary for River Rch & Prof#=P156-00-00,P156-00-00_0009, 4
Up Type= 0
Dn Type= 3
Dn Slope= 0.00400

--- P156-00-00.g01 (geometry) ---

Geom Title=P156-00-00 June 2007
Version=Version 3.0.1  Mar 2001

River Reach=P156-00-00      ,P156-00-00_0009
Reach XY= 9
      3111984.87     13915081.23        3112006.       13914999.
        3112649.       13912403.      3112665.75       13912335.
      3112685.75       13912269.        3112721.       13912209.
      3112751.75       13912139.       3112762.5       13912081.
        3112987.       13911145.

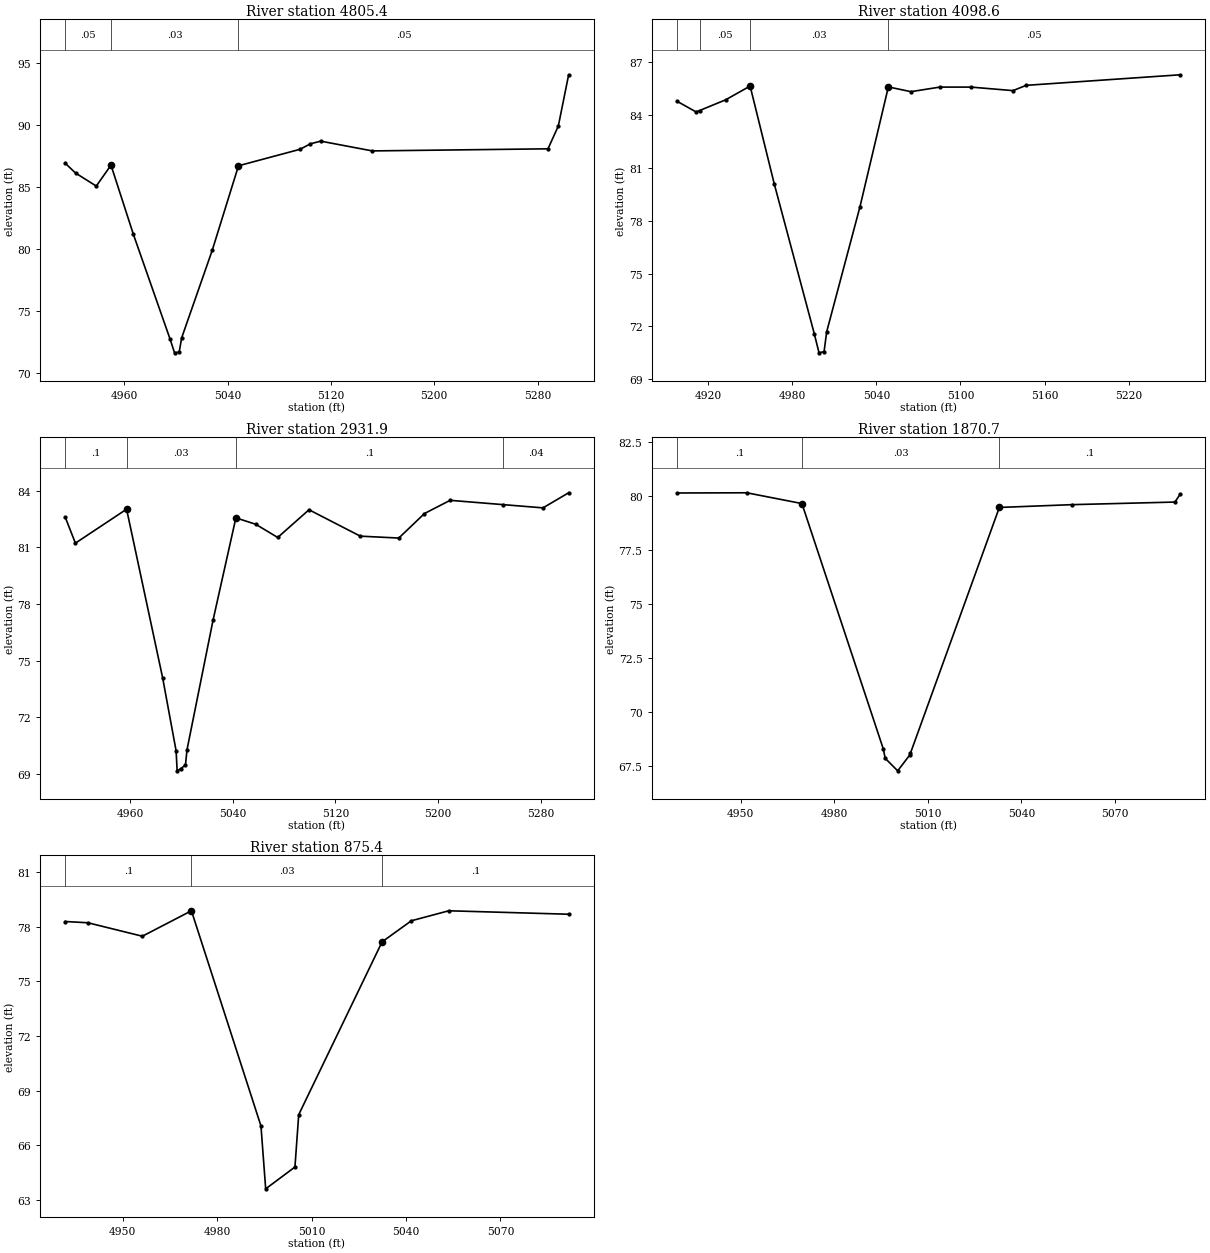
Type RM Length L Ch R = 1 ,4805.4  ,709.3,706.8,705.8
BEGIN DESCRIPTION:
Cross Section 4805.4-Interpolated
END DESCRIPTION:
XS GIS Cut Line= 4
       3112068.9     13915097.75      3112010.31     13915086.24
      3111945.56     13915073.53      3111686.47     13915022.64
#Sta/Elev= 18
  4914.4   86.93  4922.4   86.14  4938.4   85.09  4949.8   86.78  4967.1    81.2
  4995.6   72.71    4999   71.62  5002.6   71.69  5004.5   72.83  5028.2   79.91
  5048.5   86.73  5096.1   88.06  5104.1    88.5  5112.1   88.72  5152.1   87.93
  5288.1    88.1  5296.1   89.94  5304.1   94.08
#Mann= 3 , 1 , 0
  4914.4     .05       0  4949.8     .03       0  5048.5     .05       0
Bank Sta=4949.8,5048.5
XS Rating Curve= 0
Exp/Cntr=.3,.1

Type RM Length L Ch R = 1 ,4098.6  ,1168.5,1166.7,1165.5
BEGIN DESCRIPTION:
Cross Section 4098.6
END DESCRIPTION:
XS GIS Cut Line= 3
        3112253.     13914427.02      3112015.84     13914349.84
      3111907.16     13914332.86
#Sta/Elev= 18
  4897.5    84.8  4911.2   84.19  4913.8   84.27  4932.4   84.88  4949.8   85.66
  4967.1   80.08  4995.6   71.59    4999    70.5  5002.6   70.57  5004.5   71.71
  5028.2   78.79  5048.5   85.61  5064.6   85.34  5085.2    85.6  5107.5    85.6
  5137.5    85.4  5146.9    85.7  5256.9    86.3
#Mann= 4 , 1 , 0
  4897.5      .1       0  4913.8     .05       0  4949.8     .03       0
  5048.5     .05       0
Bank Sta=4949.8,5048.5
XS Rating Curve= 0
Exp/Cntr=.3,.1

Type RM Length L Ch R = 1 ,2931.9  ,1060.7,1061.2,1061.7
BEGIN DESCRIPTION:
Cross Section 2931.9
END DESCRIPTION:
XS GIS Cut Line= 3
      3112522.66     13913289.38      3112204.65     13913192.71
      3112147.25     13913175.19
#Sta/Elev= 21
  4909.4    82.6  4917.3   81.23  4957.2   83.03  4985.3   74.09  4995.8   70.22
  4996.6   69.16  4999.3   69.27  5003.1   69.47  5004.3   70.28  5024.6   77.15
  5042.4   82.57  5057.9   82.23    5075   81.53  5099.4      83  5139.4    81.6
  5169.4    81.5  5189.4    82.8  5209.4    83.5    5251   83.27  5281.8    83.1
  5301.8    83.9
#Mann= 4 , 1 , 0
  4909.4      .1       0  4957.2     .03       0  5042.4      .1       0
    5251     .04       0
Bank Sta=4957.2,5042.4
XS Rating Curve= 0
Exp/Cntr=.3,.1

Type RM Length L Ch R = 1 ,1870.7  ,995.3,995.3,993.9
BEGIN DESCRIPTION:
Cross Section 1870.7
END DESCRIPTION:
XS GIS Cut Line= 2
      3112771.87     13912257.32      3112616.89     13912212.27
#Sta/Elev= 12
  4929.5   80.15  4951.9   80.16  4969.6   79.66  4995.7   68.28  4996.3   67.85
  5000.3   67.27  5004.1   67.99  5004.4   68.09  5032.9   79.48  5056.3   79.61
  5089.2   79.73  5090.9    80.1
#Mann= 3 , 1 , 0
  4929.5      .1       0  4969.6     .03       0  5032.9      .1       0
Bank Sta=4969.6,5032.9
XS Rating Curve= 0
Exp/Cntr=.3,.1

Type RM Length L Ch R = 1 ,875.4   ,0,0,0
BEGIN DESCRIPTION:
Cross Section 875.4
END DESCRIPTION:
XS GIS Cut Line= 2
      3113021.44     13911294.22      3112866.49     13911254.34
#Sta/Elev= 12
  4931.7    78.3  4938.9   78.23  4956.2   77.49  4971.8   78.89  4993.9   67.05
  4995.4   63.59  5004.7   64.79  5005.9   67.67  5032.4   77.18  5041.7   78.34
  5053.6   78.89  5091.7    78.7
#Mann= 3 , 1 , 0
  4931.7      .1       0  4971.8     .03       0  5032.4      .1       0
Bank Sta=4971.8,5032.4
XS Rating Curve= 0
Exp/Cntr=.3,.1

Chan Stop Cuts=-1